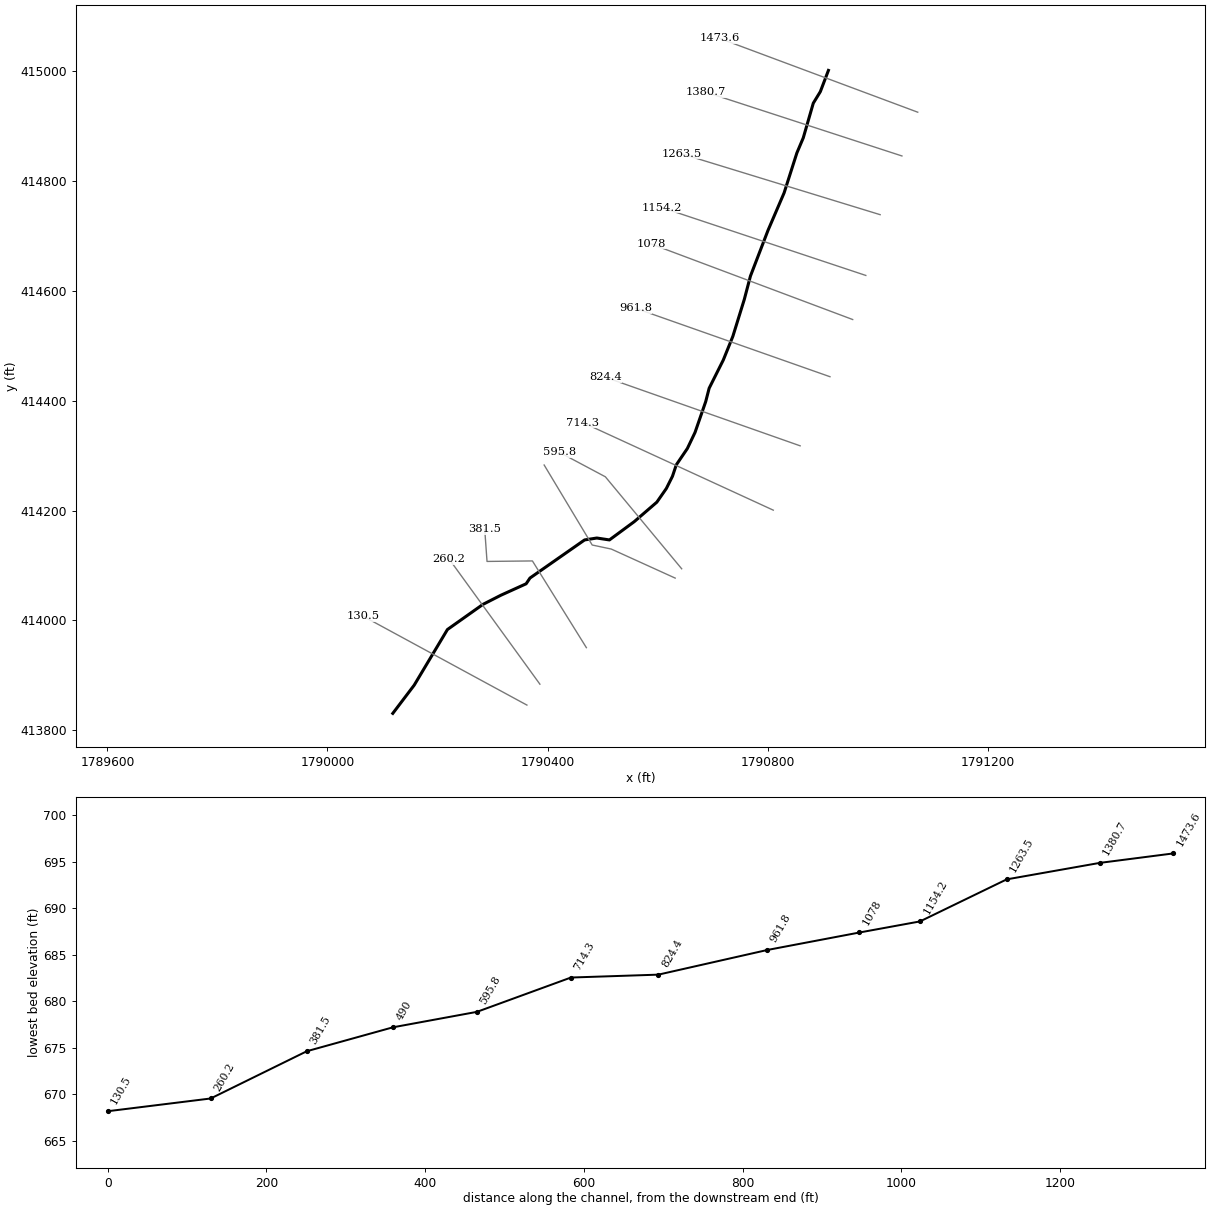
--- JOESBR.prj (project) ---

Proj Title=JOESBR
Current Plan=p01
Default Exp/Contr=0,0
English Units
Geom File=g01
Flow File=f01
Plan File=p01
BEGIN DESCRIPTION:
END DESCRIPTION:
DSS Export Rating Curves= 0
DSS Export Rating Curve Sorted= 0
DSS Export Volume Flow Curves= 0
DXF OffsetX= 0
DXF OffsetY= 0
DXF ScaleX= 0
DXF ScaleY= 0

--- JOESBR.p01 (plan) ---

Plan Title=Floodplain
Program Version=4.00
Geom File=g01
Flow File=f01
K Sum by GR=0
Std Step Tol=0.01
Critical Tol=0.01
Num of Std Step Trials=20
Max Error Tol=0.3
Flow Tol Ratio=0.001
Split Flow NTrial=30
Split Flow Tol=0.02
Split Flow Ratio=0.02
Log Output Level=0
Friction Slope Method=1
Unsteady Friction Slope Method=2
Unsteady Bridges Friction Slope Method=1
Global Log Level=0
CheckData=False
Run HTab=0
Run UNet=0
Run PostProcess=0
UNET Theta=0
UNET Theta Warmup=0
UNET ZTol=0
UNET ZSATol=0
UNET MxIter=0
UNET MaxInSteps=0
UNET DtIC=0
UNET DtMin=0
UNET MaxCRTS=0
UNET WFStab=0
UNET SFStab=0
UNET WFX=0
UNET SFX=0
UNET DSS MLevel=0
UNET DZMax Abort=0
UNET Convert EG Bridges=0
UNET Use Existing IB Tables=0
UNET Froude Limit=0
UNET Froude Power=0
Write IC File=0
Echo Input=False
Echo Output=False
Write Detailed=0

--- JOESBR.f01 (steady flow) ---

Flow Title=NFF Regression Equation
Program Version=5.03
Number of Profiles= 1
Profile Names=P100yr
River Rch & RM=JOESBR,Main            ,1473.6
 896.334
River Rch & RM=JOESBR,Main            ,595.8
 914.115
River Rch & RM=JOESBR,Main            ,260.2
 915.598
Boundary for River Rch & Prof#=JOESBR,Main            , 1
Up Type= 0
Dn Type= 3
Dn Slope=0.00915
DSS Import GetInterval= 0
DSS Import GetPeak= 0
DSS Import FillOption= 0

--- JOESBR.g01 (geometry) ---

Geom Title=USGS 10m DEM
Program Version=5.03

River Reach=JOESBR          ,Main
Reach XY= 30
     1790910.525       415001.89     1790895.802      414963.145
     1790883.016      414942.222     1790864.806      414879.067
     1790853.182      414851.558     1790829.935      414778.716
     1790800.693      414710.531     1790768.749      414627.198
     1790757.638      414584.837     1790736.804      414517.475
     1790719.443       414474.42     1790693.749      414423.031
     1790687.499      414398.725     1790668.054      414342.476
     1790654.166      414313.309     1790634.027      414283.517
     1790627.082      414262.684     1790615.971      414240.462
      1790598.61      414215.462     1790557.638      414180.045
     1790512.499      414146.712     1790489.582      414150.184
      1790467.36      414146.712     1790368.054      414077.267
      1790361.11       414066.85     1790315.277      414046.017
     1790282.638       414029.35     1790218.054      413983.517
     1790157.637      413882.198     1790118.749      413830.809

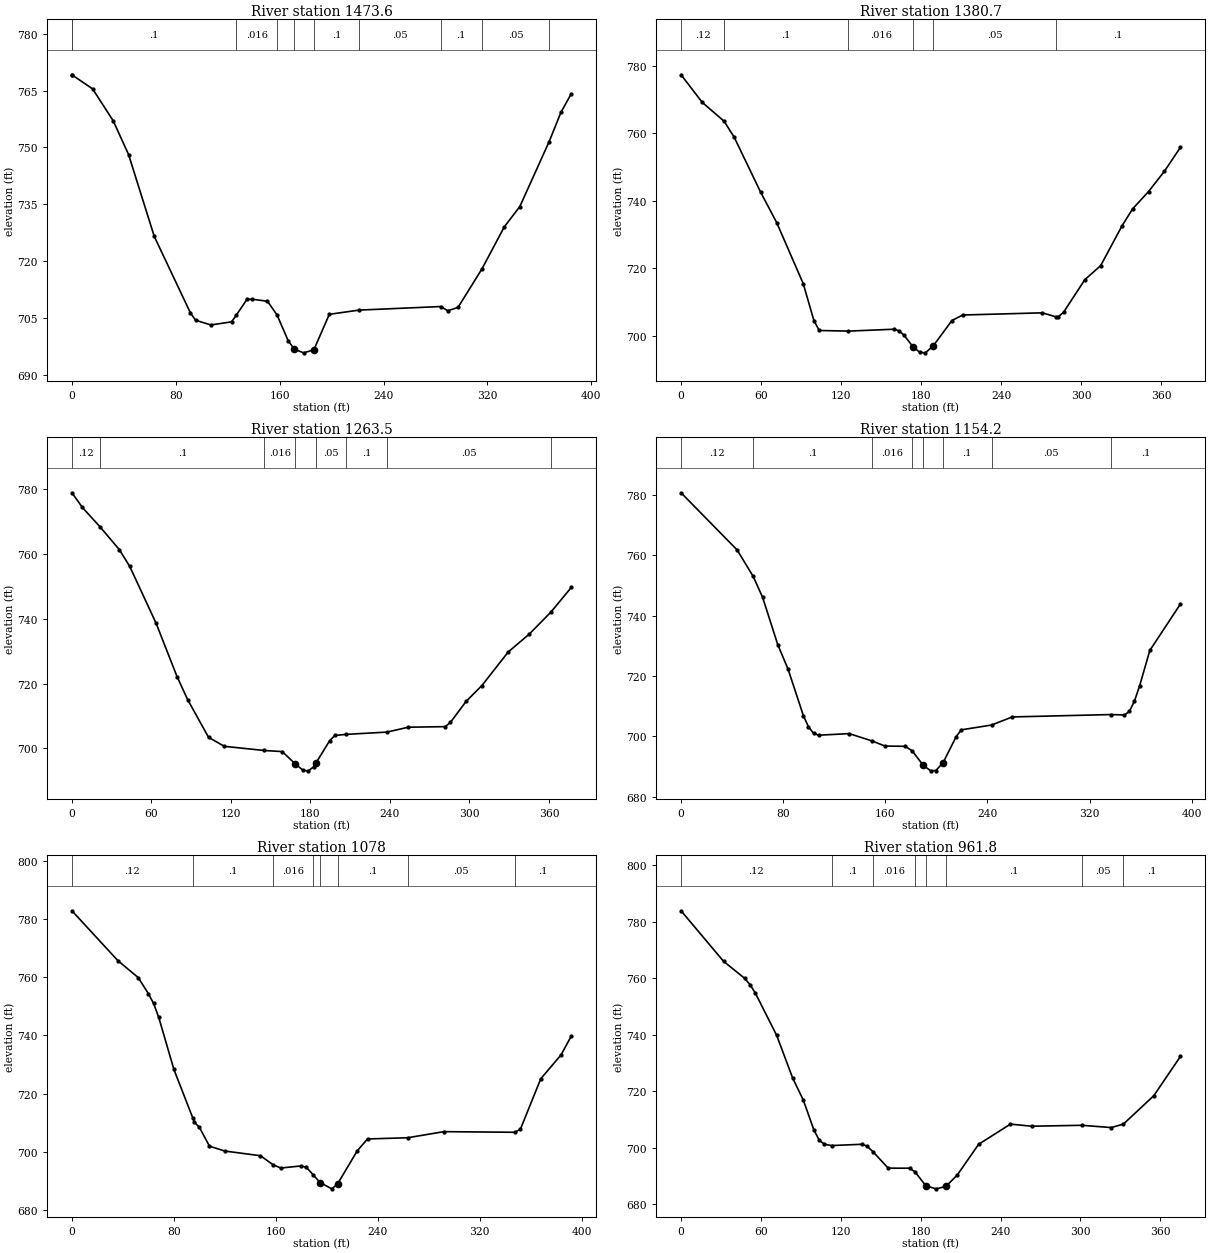
Type RM Length L Ch R = 1 ,1473.6  ,91.9,92.9,93.9
XS GIS Cut Line= 2
     1791072.879       414925.76     1790712.636      415060.308
#Sta/Elev= 30
       0  769.15     .33 769.056    15.9  765.44    31.7  757.07    43.6  748.14
    63.4  726.56    91.2  706.44    95.2  704.48     107  703.24   122.9  704.05
  126.45705.7451   134.8  709.99   138.8  710.02   150.6  709.48  157.98705.8616
   166.5   699.1   171.3  696.86   178.4  695.89   186.3  696.68   198.2  706.04
  221.04707.1476  284.09 708.092   289.4  706.97   297.3  707.85  315.62717.9251
     333   729.1   344.9  734.41  367.46751.4952   376.6  759.26   384.6  764.19
#Mann= 10 ,-1 , 0
       0     .12       0     .33      .1       0  126.45    .016       0
  157.98      .1       0   171.3    .045       0   186.3      .1       0
  221.04     .05       0  284.09      .1       0  315.62     .05       0
  367.46      .1       0
Bank Sta=171.3,186.3
XS Rating Curve= 0 ,0
Exp/Cntr=0.3,0.1

Type RM Length L Ch R = 1 ,1380.7  ,116.7,117.2,117.5
XS GIS Cut Line= 2
     1791044.147      414846.072     1790688.244      414962.175
#Sta/Elev= 30
       0  777.35    15.9  769.16   32.24763.5822    39.8  758.86    59.7  742.49
    71.7   733.5    91.6  715.39    99.6  704.45   103.6   701.5  125.45 701.315
   159.3  701.87   163.3  701.43   167.3  700.05   174.1  696.56   179.2  694.98
   183.2  694.87   189.1  696.96   203.1  704.45   211.1  706.09   270.8  706.74
  280.79705.5751   282.8  705.56   286.8  706.92   302.7  716.56   314.6  720.74
   330.6  732.54   338.5  737.56   350.5  742.72   362.4  748.74   374.4  755.83
#Mann= 6 ,-1 , 0
       0     .12       0   32.24      .1       0  125.45    .016       0
   174.1    .045       0   189.1     .05       0  280.79      .1       0
Bank Sta=174.1,189.1
XS Rating Curve= 0 ,0
Exp/Cntr=0.3,0.1

Type RM Length L Ch R = 1 ,1263.5  ,109.7,109.3,108.7
XS GIS Cut Line= 2
      1791004.52      414739.128     1790644.277      414849.805
#Sta/Elev= 30
       0  778.87     7.9  774.33   21.51768.2104    35.7  761.37    43.6  756.17
    63.5  738.63    79.3  722.19    87.3  715.08   103.1  703.44     115  700.66
  145.11699.3753   158.7  699.04  168.52  695.24   174.6  693.22   178.5   693.1
   182.5  694.39  184.17  695.52   194.4  702.33   198.4  704.01   206.9704.3484
   237.8705.0535   253.9  706.56   281.6  706.73   285.6  708.02   297.5  714.54
   309.4  719.41   329.3  729.78   345.1  735.26  361.39742.0258   376.9  749.68
#Mann= 8 ,-1 , 0
       0     .12       0   21.51      .1       0  145.11    .016       0
  168.52    .045       0  184.17     .05       0   206.9      .1       0
   237.8     .05       0  361.39      .1       0
Bank Sta=168.52,184.17
XS Rating Curve= 0 ,0
Exp/Cntr=0.3,0.1

Type RM Length L Ch R = 1 ,1154.2  ,77.1,76.2,75.4
XS GIS Cut Line= 2
     1790978.478      414628.451     1790607.385      414752.149
#Sta/Elev= 30
       0  780.67    43.9  761.75   56.49752.9807    63.9  746.03    75.8  730.32
    83.8  722.29    95.8  706.89    99.8  703.17   103.8     701   107.8  700.38
   131.7  700.91  149.89 698.441   159.7  696.79   175.6   696.7  181.03695.2114
  189.84  690.35   195.6  688.58   199.6  688.69  205.17  691.21   215.5  699.88
   219.5  702.16   243.3 703.753   259.4  706.43   336.7 707.221   347.3  707.08
   351.2  708.25   355.2  711.74   359.2   716.7   367.2  728.44   391.2  743.84
#Mann= 8 ,-1 , 0
       0     .12       0   56.49      .1       0  149.89    .016       0
  181.03      .1       0  189.84    .045       0  205.17      .1       0
   243.3     .05       0   336.7      .1       0
Bank Sta=189.84,205.17
XS Rating Curve= 0 ,0
Exp/Cntr=0.3,0.1

Type RM Length L Ch R = 1 ,1078    ,115.8,116.2,116.7
XS GIS Cut Line= 2
     1790954.607      414548.155     1790587.853      414685.959
#Sta/Elev= 30
       0  782.79      36   765.7      52  759.87      60  754.34      64  751.03
      68  746.35      80  728.34   94.86 711.658      96  710.29     100  708.48
   107.9  702.03   119.9  700.36   147.9  698.75  157.96695.6014   163.9  694.54
   179.9  695.25   183.9  694.77  189.51692.0924  194.74  689.52   203.9  687.39
   208.4  689.08   223.9  700.48   231.9   704.5  263.47704.9232   291.8  707.01
  347.27706.7959   351.8  707.81   367.8  725.13   383.8   733.4   391.8  739.86
#Mann= 8 ,-1 , 0
       0     .12       0   94.86      .1       0  157.96    .016       0
  189.51      .1       0  194.74    .045       0   208.4      .1       0
  263.47     .05       0  347.27      .1       0
Bank Sta=194.74,208.4
XS Rating Curve= 0 ,0
Exp/Cntr=0.3,0.1

Type RM Length L Ch R = 1 ,961.8   ,137.2,137.3,137.2
XS GIS Cut Line= 2
     1790913.374      414443.989     1790559.642      414568.772
#Sta/Elev= 30
       0  783.95    31.9  766.07    47.9  759.99    51.9  757.73    55.9  754.72
    71.8  739.87    83.8  724.77    91.8  716.95    99.8  706.34   103.8  702.72
   107.7  701.29  113.08700.8337   135.7  701.28   139.7  700.66   144.4 698.522
   155.6  692.83   171.6  692.82  175.72691.5183   183.9  686.58   191.5  685.51
   198.9  686.35   207.5  690.42   223.5  701.28   247.4  708.42   263.4  707.68
  300.99708.0052   323.2   707.2  332.31 708.454   355.1  718.49   375.1   732.4
#Mann= 8 ,-1 , 0
       0     .12       0  113.08      .1       0   144.4    .016       0
  175.72      .1       0   183.9    .045       0   198.9      .1       0
  300.99     .05       0  332.31      .1       0
Bank Sta=183.9,198.9
XS Rating Curve= 0 ,0
Exp/Cntr=0.3,0.1

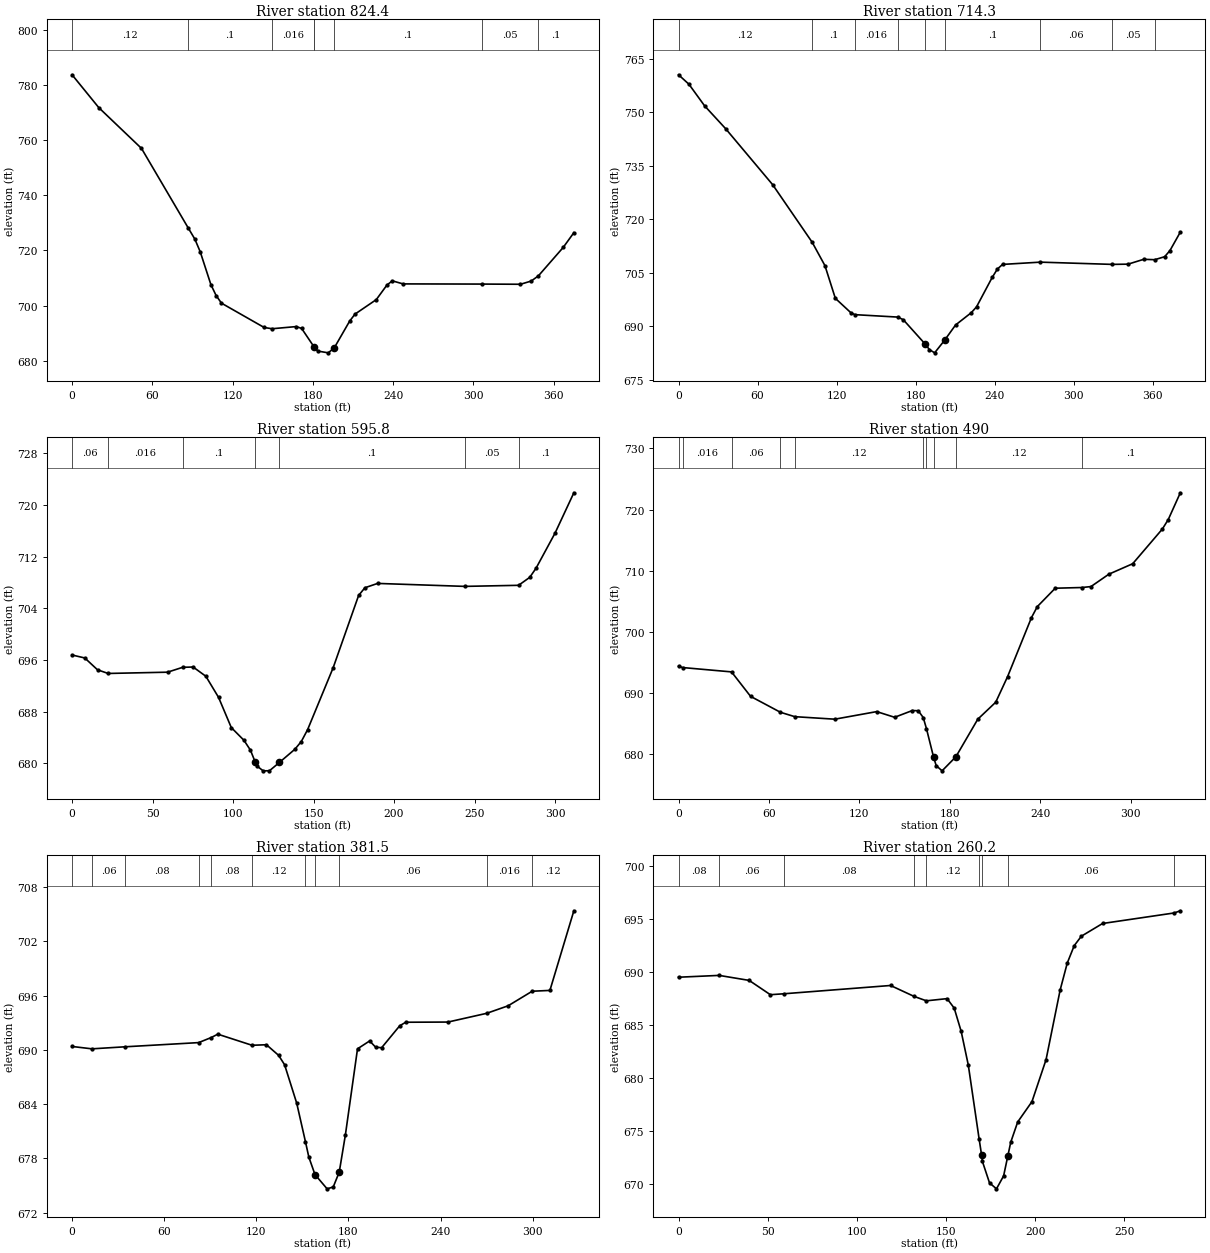
Type RM Length L Ch R = 1 ,824.4   ,112.1,110.1,108
XS GIS Cut Line= 2
     1790859.121      414318.121     1790505.388      414442.904
#Sta/Elev= 30
       0  783.66      20  771.74    51.9  756.97   86.87728.0924    91.8  724.07
    95.8  719.49   103.8  707.56   107.7  703.62   111.7  700.86   143.6  692.05
  149.51691.5959   167.6  692.38   171.6  691.71  180.83685.0547     181  684.96
   183.6  683.51   191.5  682.86     196  684.67   207.5  694.36   211.5   696.9
   227.4  702.15   235.4  707.45   239.4  708.96   247.4  707.85  306.11707.7881
   335.2  707.72   343.2  708.88  348.55 710.748   367.1  721.05   375.1  726.42
#Mann= 8 ,-1 , 0
       0     .12       0   86.87      .1       0  149.51    .016       0
  180.83      .1       0     181    .045       0     196      .1       0
  306.11     .05       0  348.55      .1       0
Bank Sta=181,196
XS Rating Curve= 0 ,0
Exp/Cntr=0.3,0.1

Type RM Length L Ch R = 1 ,714.3   ,128.6,118.5,108.3
XS GIS Cut Line= 2
     1790810.293      414200.933     1790464.155      414360.438
#Sta/Elev= 30
       0  760.53     7.9  757.88    19.8  751.82    35.7  745.44    71.5   729.7
  101.48713.5692   111.2     707   119.1  697.83     131  693.76     134693.2575
  166.52692.5774   170.7  691.84     187  685.14   190.6  683.45   194.5  682.55
     202  686.05   210.4  690.36   222.3   693.8   226.3  695.43   238.2  703.69
   242.2  706.07   246.1  707.35  274.77707.9852  329.13707.3582   341.4  707.42
   353.3  708.78  361.65708.6696   369.2  709.51   373.2  711.22   381.1  716.41
#Mann= 9 ,-1 , 0
       0     .12       0  101.48      .1       0     134    .016       0
  166.52      .1       0     187    .045       0     202      .1       0
  274.77     .06       0  329.13     .05       0  361.65      .1       0
Bank Sta=187,202
XS Rating Curve= 0 ,0
Exp/Cntr=0.3,0.1

Type RM Length L Ch R = 1 ,595.8   ,72.2,105.8,102
XS GIS Cut Line= 3
     1790643.802      414094.168     1790505.079      414261.734
     1790421.968      414306.084
#Sta/Elev= 30
       0  696.79     7.9  696.33    15.8   694.5    22.4693.9333    59.3  694.13
   68.71694.8853    75.2  694.93    83.1   693.5      91  690.23    98.9  685.56
   106.8  683.58   110.8  682.06   113.8   680.2   114.7  679.64   118.7  678.86
   122.6  678.87   128.8  680.16   138.4   682.2   142.4   683.4   146.3  685.23
   162.2  694.83     178  706.01   181.9   707.2   189.8  707.87  243.88707.4115
  277.35707.5769   284.3  708.81   288.2  710.22     300  715.65   311.7   721.9
#Mann= 7 ,-1 , 0
       0     .06       0    22.4    .016       0   68.71      .1       0
   113.8    .045       0   128.8      .1       0  243.88     .05       0
  277.35      .1       0
Bank Sta=113.8,128.8
XS Rating Curve= 0 ,0
Exp/Cntr=0.3,0.1

Type RM Length L Ch R = 1 ,490     ,145.7,108.5,108.6
XS GIS Cut Line= 4
     1790631.994      414077.206     1790515.892      414130.085
     1790481.169      414137.464     1790393.843      414283.182
#Sta/Elev= 30
       0  694.34    2.72694.1156   35.17 693.404    47.8   689.4   67.63686.7894
   77.13686.0718   103.7  685.66   131.5   686.9   143.4  685.97   155.2  687.08
   159.1  687.04  162.39685.9296  164.53684.1097  169.26  679.44     171  678.05
   174.9   677.2  184.07  679.51   198.6  685.66   210.5  688.44   218.4  692.65
   234.2  702.29   238.1   704.1     250  707.11  267.83707.2252   273.7  707.38
   285.6  709.41   301.4  711.12   321.1  716.81     325  718.36     333  722.74
#Mann= 10 ,-1 , 0
       0     .06       0    2.72    .016       0   35.17     .06       0
   67.63    .016       0   77.13     .12       0  162.39    .016       0
  164.53     .12       0  169.26    .045       0  184.07     .12       0
  267.83      .1       0
Bank Sta=169.26,184.07
XS Rating Curve= 0 ,0
Exp/Cntr=0.3,0.1

Type RM Length L Ch R = 1 ,381.5   ,119.8,121.2,122.6
XS GIS Cut Line= 4
     1790470.579      413950.528     1790372.532      414108.456
     1790290.007      414107.549     1790285.857      414165.806
#Sta/Elev= 30
       0  690.38   12.91690.1174   34.65690.3444   82.44690.8068   90.65691.3698
    94.9  691.74  117.21690.5115   126.6  690.57   134.5   689.4   138.4  688.36
   146.3  684.11  151.97679.8611   154.2  678.14   158.2  676.21   166.1  674.63
   170.1  674.84     174  676.48     178  680.59   185.9  690.12   193.8  690.99
   197.7   690.3   201.6  690.24   213.4  692.67   217.3  693.06   244.8  693.08
  270.05694.0477     284  694.88  299.66696.4901   311.2  696.58   326.8  705.39
#Mann= 11 ,-1 , 0
       0    .016       0   12.91     .06       0   34.65     .08       0
   82.44     .06       0   90.65     .08       0  117.21     .12       0
  151.97     .06       0   158.2    .045       0     174     .06       0
  270.05    .016       0  299.66     .12       0
Bank Sta=158.2,174
XS Rating Curve= 0 ,0
Exp/Cntr=0.3,0.1

Type RM Length L Ch R = 1 ,260.2   ,119.6,129.8,139.9
XS GIS Cut Line= 2
     1790386.117      413883.992     1790221.143      414111.929
#Sta/Elev= 30
       0  689.52   22.76 689.692    39.6  689.22    51.5  687.87   59.22687.9598
   118.9  688.74  132.14687.7064  138.99687.2929   150.6   687.5   154.6   686.6
   158.5  684.41   162.5  681.23   168.6674.2187  169.94  672.75   170.4  672.14
   174.4  670.11   178.3  669.55   182.3  670.77  184.61  672.61   186.3  673.95
   190.2  675.86   198.2  677.78   206.1  681.74     214  688.31     218  690.86
   221.9   692.5   225.9  693.39   237.8  694.59  277.98695.5848   281.4  695.79
#Mann= 9 ,-1 , 0
       0     .08       0   22.76     .06       0   59.22     .08       0
  132.14     .06       0  138.99     .12       0   168.6     .06       0
  169.94    .045       0  184.61     .06       0  277.98    .016       0
Bank Sta=169.94,184.61
XS Rating Curve= 0 ,0
Exp/Cntr=0.3,0.1

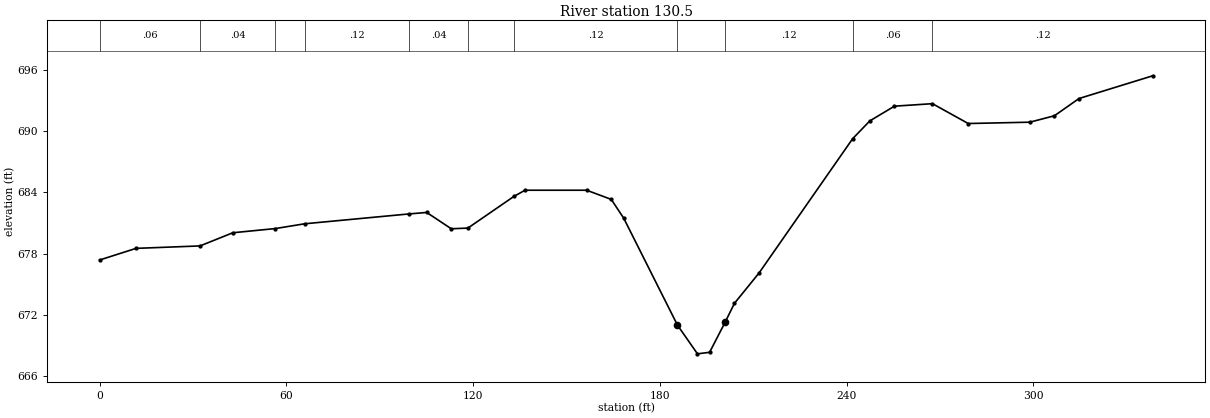
Type RM Length L Ch R = 1 ,130.5   ,133.8,130.5,127.1
XS GIS Cut Line= 3
     1790362.506      413845.913     1790277.136      413892.304
     1790065.197      414007.588
#Sta/Elev= 30
       0  677.38    11.7  678.52   32.26678.7598    42.8  680.05    56.5680.4631
   65.88680.9299   99.49681.8984   105.1  682.04     113  680.44  118.34  680.51
  133.12683.6141   136.7  684.22   156.5  684.22   164.4  683.32   168.4  681.48
  185.68  670.99   192.1  668.18     196  668.33  201.02   671.3     204  673.14
   211.9  676.11  241.97689.2735   247.5  691.02   255.4  692.46  267.61692.7047
   279.1  690.76   298.9  690.89   306.8  691.52   314.7  693.21   338.4  695.44
#Mann= 11 ,-1 , 0
       0     .06       0   32.26     .04       0    56.5     .06       0
   65.88     .12       0   99.49     .04       0  118.34     .06       0
  133.12     .12       0  185.68    .045       0  201.02     .12       0
  241.97     .06       0  267.61     .12       0
Bank Sta=185.68,201.02
XS Rating Curve= 0 ,0
Exp/Cntr=0.3,0.1
LCMann Table=0

Chan Stop Cuts=-1
Use User Specified Reach Order=0
Composite Channel Slope=5